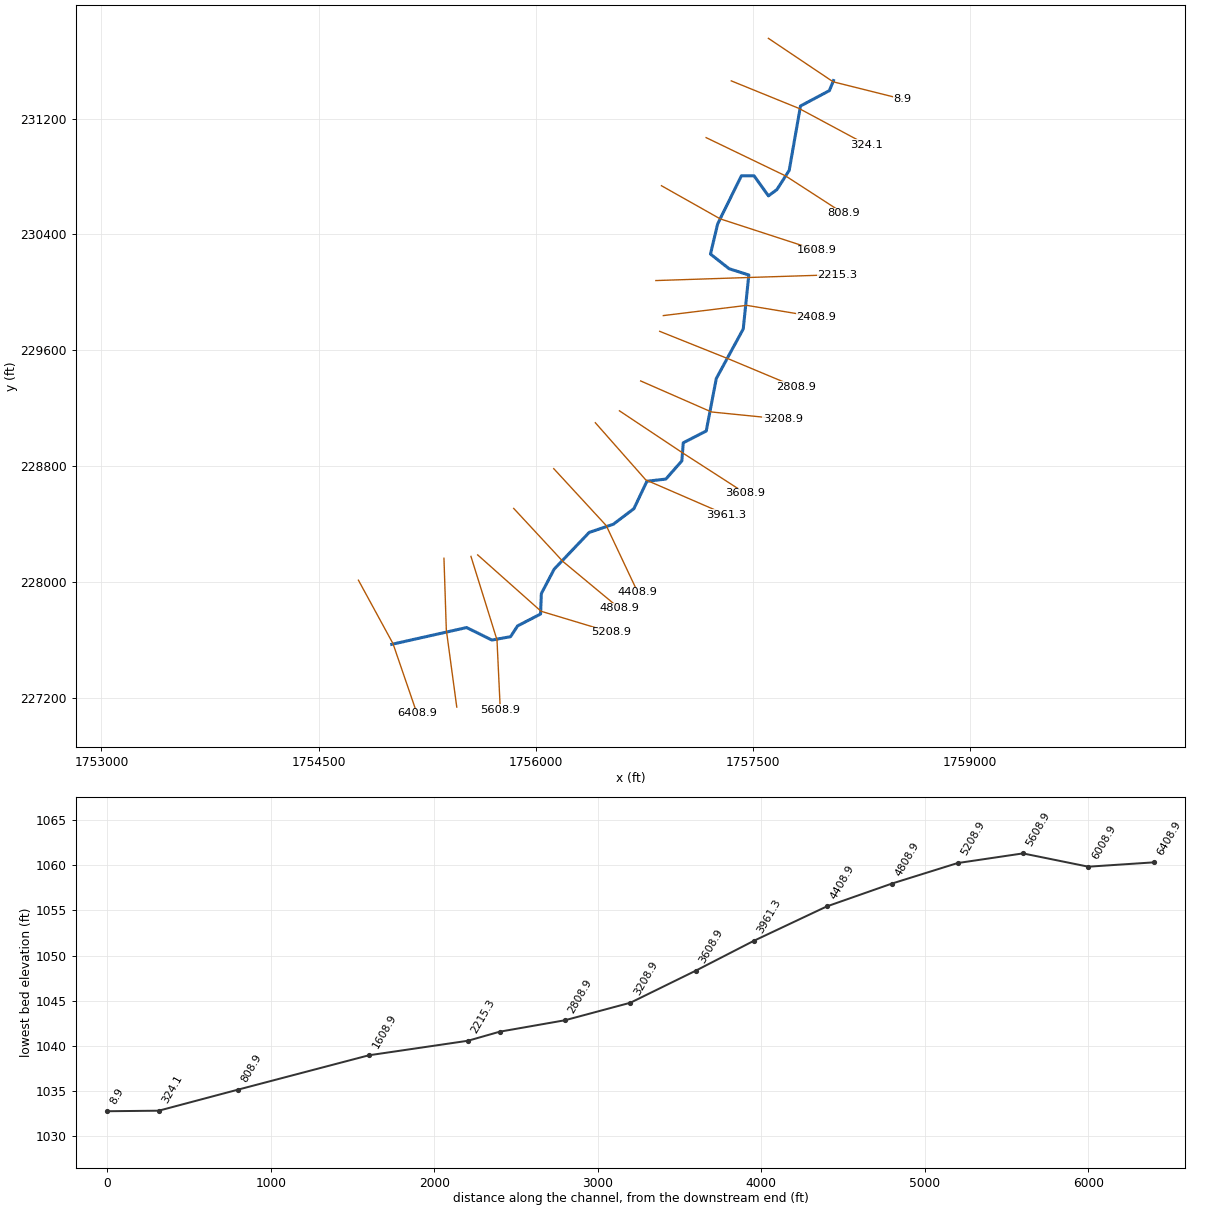
--- PeeltreRn.prj (project) ---

Proj Title=PeeltreRn
Current Plan=p01
Default Exp/Contr=0,0
English Units
Geom File=g01
Flow File=f01
Plan File=p01
BEGIN DESCRIPTION:
END DESCRIPTION:
DSS Export Rating Curves= 0
DSS Export Rating Curve Sorted= 0
DSS Export Volume Flow Curves= 0
DXF OffsetX= 0
DXF OffsetY= 0
DXF ScaleX= 0
DXF ScaleY= 0

--- PeeltreRn.p01 (plan) ---

Plan Title=Floodplain
Program Version=4.00
Geom File=g01
Flow File=f01
K Sum by GR=0
Std Step Tol=0.01
Critical Tol=0.01
Num of Std Step Trials=20
Max Error Tol=0.3
Flow Tol Ratio=0.001
Split Flow NTrial=30
Split Flow Tol=0.02
Split Flow Ratio=0.02
Log Output Level=0
Friction Slope Method=1
Unsteady Friction Slope Method=2
Unsteady Bridges Friction Slope Method=1
Global Log Level=0
CheckData=False
Run HTab=0
Run UNet=0
Run PostProcess=0
UNET Theta=0
UNET Theta Warmup=0
UNET ZTol=0
UNET ZSATol=0
UNET MxIter=0
UNET MaxInSteps=0
UNET DtIC=0
UNET DtMin=0
UNET MaxCRTS=0
UNET WFStab=0
UNET SFStab=0
UNET WFX=0
UNET SFX=0
UNET DSS MLevel=0
UNET DZMax Abort=0
UNET Convert EG Bridges=0
UNET Use Existing IB Tables=0
UNET Froude Limit=0
UNET Froude Power=0
Write IC File=0
Echo Input=False
Echo Output=False
Write Detailed=0

--- PeeltreRn.f01 (steady flow) ---

Flow Title=NFF Regression Equation
Program Version=4.00
Number of Profiles= 1
Profile Names=P100yr
River Rch & RM=PeeltreRn,Main            ,6408.9
947.4134
River Rch & RM=PeeltreRn,Main            ,3961.3
 1016.92
River Rch & RM=PeeltreRn,Main            ,3608.9
1279.405
River Rch & RM=PeeltreRn,Main            ,324.1
1319.584
River Rch & RM=PeeltreRn,Main            ,8.9
 1397.54
Boundary for River Rch & Prof#=PeeltreRn,Main            , 1
Up Type= 0
Dn Type= 3
Dn Slope=0.003961
DSS Import GetInterval= 0
DSS Import GetPeak= 0
DSS Import FillOption= 0

--- PeeltreRn.g01 (geometry) ---

Geom Title=USGS 3m DEM
Program Version=4.00

River Reach=PeeltreRn     ,Main
Reach XY= 30
     1755005.378      227568.666     1755522.718      227684.618
     1755697.351      227598.301     1755826.247      227621.567
     1755874.527      227695.839     1756033.528      227778.147
     1756038.826      227919.254     1756127.295      228087.892
     1756369.394      228341.790     1756535.634      228397.994
     1756678.328      228505.875     1756768.137      228695.242
     1756898.887      228710.286     1757009.503      228836.054
     1757019.191      228960.958     1757177.835      229042.402
     1757247.347      229404.878     1757433.482      229747.173
     1757471.985      230120.019     1757335.911      230163.174
     1757207.121      230264.644     1757256.731      230472.856
     1757420.970      230805.489     1757507.776      230805.489
     1757607.602      230666.600     1757666.196      230710.003
     1757750.831      230842.381     1757828.957      231287.260
     1758028.609      231393.597     1758056.821      231463.041

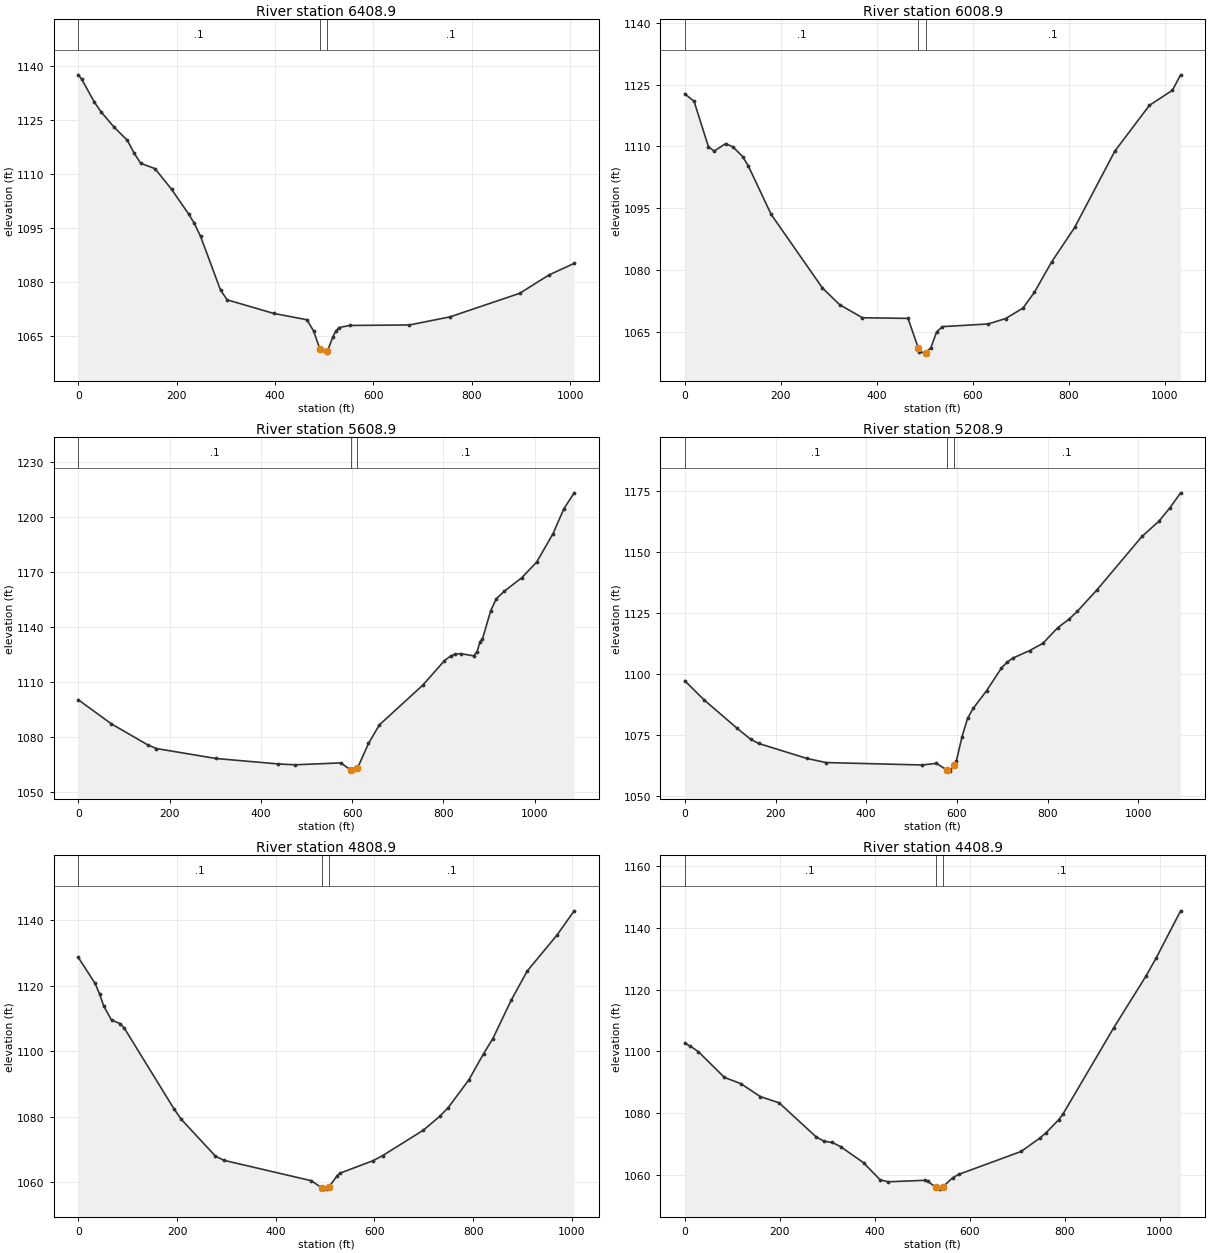
Type RM Length L Ch R = 1 ,6408.9,410.306,400,405.491
XS GIS Cut Line= 3
     1754775.394      228011.578     1755014.159      227573.451
     1755179.459      227091.812
#Sta/Elev= 30
       0 1137.56     7.1 1136.29    32.2 1130.08    45.7 1127.37    72.8 1123.03
    99.8 1119.37   113.3 1115.87   126.8 1113.01   155.9 1111.52   189.6 1105.79
   224.6 1098.86   235.0 1096.53   248.5 1092.74   289.1 1077.84   302.6 1075.11
   397.3 1071.34   464.9 1069.58   478.5 1066.42   491.5 1061.33   504.8 1060.32
   506.5 1060.84   517.5 1064.83   523.8 1066.53   530.1 1067.42   551.8 1068.00
   673.3 1068.14   756.0 1070.39   897.6 1076.93   956.9 1082.01  1008.2 1085.23
#Mann= 3 , 0 , 0
       0     0.1       0   491.5   0.045       0   506.5     0.1       0
Bank Sta=   491.5,   506.5
Exp/Cntr=0.3,0.1

Type RM Length L Ch R = 1 ,6008.9,394.677,400,398.971
XS GIS Cut Line= 3
     1755366.159      228163.169     1755382.463      227669.244
     1755454.648      227135.169
#Sta/Elev= 30
       0 1122.75    19.3 1120.95    49.3 1109.90    61.2 1108.88    84.9 1110.66
    99.8 1109.94   120.6 1107.54   132.4 1105.24   180.0 1093.49   286.9 1075.63
   322.5 1071.61   370.0 1068.43   465.1 1068.27   486.7 1061.00   488.8 1060.22
   500.8 1059.84   501.7 1059.94   512.7 1061.14   524.7 1064.98   536.7 1066.27
   632.5 1066.92   668.5 1068.24   704.4 1070.75   728.4 1074.59   764.3 1081.96
   812.3 1090.33   896.1 1108.87   968.0 1119.96  1015.9 1123.62  1033.1 1127.37
#Mann= 3 , 0 , 0
       0     0.1       0   486.7   0.045       0   501.7     0.1       0
Bank Sta=   486.7,   501.7
Exp/Cntr=0.3,0.1

Type RM Length L Ch R = 1 ,5608.9,389.53,400,427.14
XS GIS Cut Line= 3
     1755552.684      228176.091     1755732.482      227599.316
     1755755.221      227117.656
#Sta/Elev= 30
       0 1100.28    72.4 1087.13   152.2 1075.64   171.2 1073.64   301.4 1068.22
   438.2 1065.23   474.5 1064.77   575.0 1065.80   596.6 1061.97   599.9 1061.31
   611.6 1062.89   635.7 1076.43   659.5 1086.55   754.6 1108.26   802.1 1121.62
   816.0 1124.31   825.9 1125.15   837.8 1125.48   865.9 1124.28   873.5 1126.52
   880.3 1132.08   885.3 1133.40   903.4 1148.88   915.8 1155.49   932.9 1159.51
   971.1 1166.85  1004.2 1175.51  1039.9 1190.99  1063.6 1204.52  1086.3 1213.32
#Mann= 3 , 0 , 0
       0     0.1       0   596.6   0.045       0   611.6     0.1       0
Bank Sta=   596.6,   611.6
Exp/Cntr=0.3,0.1

Type RM Length L Ch R = 1 ,5208.9,400.803,400,390.806
XS GIS Cut Line= 3
     1755599.003      228186.533     1756036.555      227797.297
     1756522.565      227650.917
#Sta/Elev= 30
       0 1097.27    42.3 1089.46   114.6 1077.92   145.0 1073.31   162.9 1071.57
   268.8 1065.46   311.4 1063.75   523.0 1062.76   554.8 1063.42   578.1 1060.67
   585.6 1060.24   593.1 1062.55   598.5 1064.22   611.2 1074.30   623.6 1081.95
   636.0 1085.97   665.6 1093.26   698.0 1102.45   710.4 1104.85   722.8 1106.52
   760.0 1109.61   789.5 1112.59   822.0 1118.96   846.8 1122.44   865.7 1125.76
   908.8 1134.51  1008.0 1156.40  1045.2 1162.60  1070.0 1168.23  1093.2 1174.26
#Mann= 3 , 0 , 0
       0     0.1       0   578.1   0.045       0   593.1     0.1       0
Bank Sta=   578.1,   593.1
Exp/Cntr=0.3,0.1

Type RM Length L Ch R = 1 ,4808.9,400.197,400,389.684
XS GIS Cut Line= 3
     1755847.935      228507.531     1756188.417      228140.667
     1756576.402      227818.645
#Sta/Elev= 30
       0 1128.57    34.0 1120.63    42.9 1117.50    51.4 1113.79    67.3 1109.46
    84.9 1108.41    93.3 1107.00   194.1 1082.37   208.5 1079.27   277.9 1068.02
   295.8 1066.73   472.2 1060.54     493 1058.40   496.5 1057.98   504.7 1058.05
     508 1058.66   523.8 1061.93   530.2 1062.84   597.3 1066.65   616.8 1068.21
   698.9 1075.91   732.6 1080.20   749.4 1082.79   791.6 1091.34   821.3 1099.29
   839.9 1103.83   877.0 1115.50   909.6 1124.44   970.0 1135.39  1004.7 1142.77
#Mann= 3 , 0 , 0
       0     0.1       0     493   0.045       0     508     0.1       0
Bank Sta=     493,     508
Exp/Cntr=0.3,0.1

Type RM Length L Ch R = 1 ,4408.9,442.506,447.619,472.686
XS GIS Cut Line= 3
     1756124.607      228782.217     1756487.471      228388.617
     1756704.345      227929.049
#Sta/Elev= 30
       0 1102.60    11.3 1101.77    28.8 1099.89    83.5 1091.57   117.7 1089.60
   159.1 1085.37   198.5 1083.37   276.7 1072.31   293.5 1070.93   310.3 1070.54
   327.7 1069.21   376.1 1064.00   411.2 1058.44   428.0 1057.82   505.3 1058.29
   512.0 1057.93   527.8 1056.06   537.2 1055.44   542.8 1056.11   563.4 1059.10
   576.5 1060.21   707.8 1067.63   747.2 1071.95   760.2 1073.67   786.6 1077.83
   796.0 1079.77   903.0 1107.72   970.4 1124.35   992.2 1130.29  1043.5 1145.50
#Mann= 3 , 0 , 0
       0     0.1       0   527.8   0.045       0   542.8     0.1       0
Bank Sta=   527.8,   542.8
Exp/Cntr=0.3,0.1

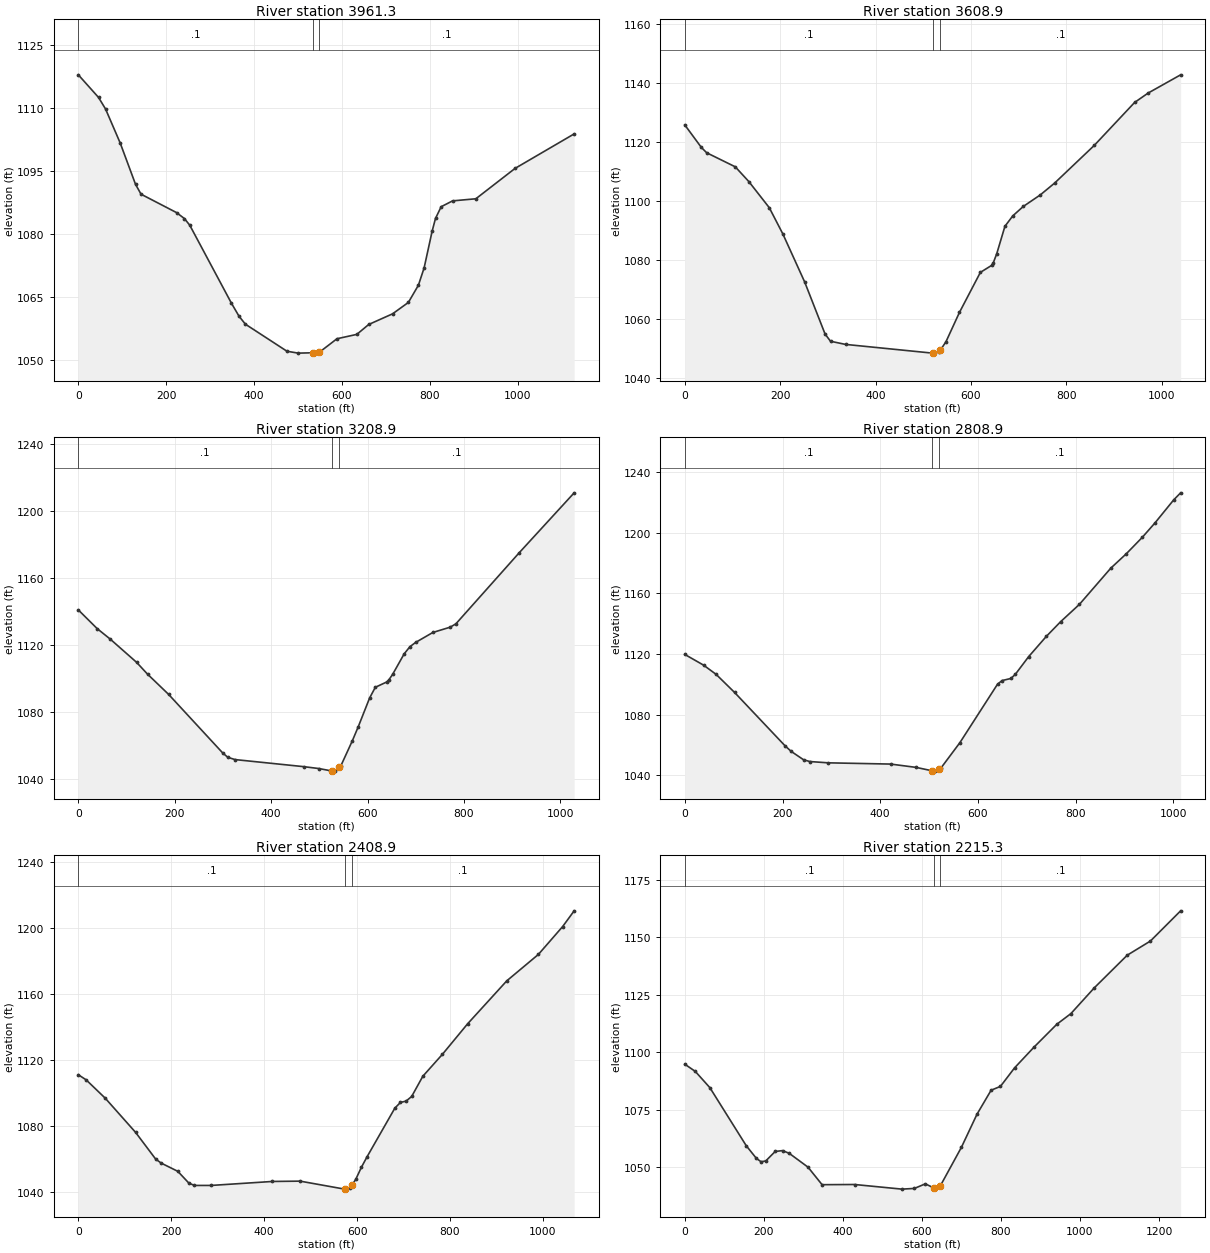
Type RM Length L Ch R = 1 ,3961.3,354.548,352.381,337.943
XS GIS Cut Line= 3
     1756411.812      229099.457     1756760.255      228704.604
     1757312.222      228465.291
#Sta/Elev= 30
       0 1117.81    46.0 1112.43    62.0 1109.67    95.2 1101.61   130.1 1091.78
   142.7 1089.42   223.5 1085.04   241.4 1083.62   253.5 1082.05   348.5 1063.47
   365.6 1060.40   380.2 1058.50   474.7 1052.07   500.2 1051.62   533.2 1051.70
   548.2 1051.81   588.5 1055.04   633.7 1056.08   660.7 1058.43   714.9 1060.96
   751.0 1063.68   773.8 1067.77   786.8 1071.89   805.2 1080.69   812.7 1083.66
   825.6 1086.44   851.5 1087.83   904.5 1088.33   993.8 1095.56  1128.2 1103.76
#Mann= 3 , 0 , 0
       0     0.1       0   533.2   0.045       0   548.2     0.1       0
Bank Sta=   533.2,   548.2
Exp/Cntr=0.3,0.1

Type RM Length L Ch R = 1 ,3608.9,394.902,400,411.846
XS GIS Cut Line= 3
     1756578.387      229181.734     1757018.350      228888.854
     1757448.165      228611.897
#Sta/Elev= 30
       0 1125.78    34.6 1118.17    45.9 1116.33   105.9 1111.56   134.4 1106.54
   177.2 1097.69   205.7 1088.77   251.4 1072.49   294.2 1054.82   305.6 1052.37
   337.1 1051.30   519.5 1048.34     521 1048.39   533.7 1048.82     536 1049.35
   547.8 1052.22   576.1 1062.18   619.9 1075.74   644.1 1078.17   646.7 1078.85
   654.3 1082.10   671.4 1091.38   687.9 1094.92   709.8 1098.10   745.6 1102.03
   775.6 1106.04   858.6 1118.80   943.3 1133.39   971.6 1136.58  1039.9 1142.78
#Mann= 3 , 0 , 0
       0     0.1       0     521   0.045       0     536     0.1       0
Bank Sta=     521,     536
Exp/Cntr=0.3,0.1

Type RM Length L Ch R = 1 ,3208.9,399.191,400,393.185
XS GIS Cut Line= 3
     1756725.032      229388.102     1757213.939      229173.912
     1757706.092      229124.486
#Sta/Elev= 30
       0 1141.11    39.1 1129.94    65.7 1123.79   120.7 1109.84   143.5 1102.75
   187.1 1090.69   299.1 1055.76   310.0 1053.05   325.0 1051.69   467.6 1047.46
   499.3 1046.32   526.3 1044.85   532.4 1044.79   541.3 1047.16   544.4 1047.89
   568.3 1062.90   580.2 1071.02   604.1 1088.46   616.0 1094.89   639.9 1098.09
   644.1 1099.35   651.8 1102.56   675.7 1114.81   687.6 1119.11   699.5 1121.68
   735.3 1127.64   771.1 1130.79   783.1 1132.80   914.3 1175.23  1028.4 1211.08
#Mann= 3 , 0 , 0
       0     0.1       0   526.3   0.045       0   541.3     0.1       0
Bank Sta=   526.3,   541.3
Exp/Cntr=0.3,0.1

Type RM Length L Ch R = 1 ,2808.9,388.607,400,405.115
XS GIS Cut Line= 3
     1756856.318      229730.829     1757333.069      229539.969
     1757795.626      229346.565
#Sta/Elev= 30
       0 1119.80    38.5 1112.72    64.1 1106.66   101.9 1094.73   204.8 1059.68
   217.6 1055.90   243.2 1050.32   256.0 1049.17   293.5 1048.32   421.3 1047.50
   473.4 1045.32     506 1043.09   511.7 1042.85     521 1044.20   524.6 1045.02
   563.2 1061.67   640.1 1100.16   649.4 1102.56   667.5 1103.95   676.6 1106.69
   703.8 1118.32   740.1 1131.72   769.1 1141.32   807.7 1152.79   872.0 1176.69
   903.5 1186.10   936.4 1196.99   962.1 1206.39  1000.7 1221.69  1014.9 1226.35
#Mann= 3 , 0 , 0
       0     0.1       0     506   0.045       0     521     0.1       0
Bank Sta=     506,     521
Exp/Cntr=0.3,0.1

Type RM Length L Ch R = 1 ,2408.9,195.695,193.594,198.087
XS GIS Cut Line= 3
     1756881.384      229839.515     1757457.853      229910.271
     1757937.641      229830.765
#Sta/Elev= 30
       0 1111.00    17.0 1107.85    57.9 1096.76   123.2 1076.03   166.3 1059.86
   178.3 1057.38   214.1 1052.38   238.1 1045.17   250.0 1043.82   285.9 1043.82
   417.5 1046.23   477.3 1046.43   573.0 1041.58   573.3 1041.60   585.0 1042.47
   588.3 1043.86   597.0 1047.47   609.1 1054.78   621.1 1061.06   681.3 1090.77
   693.3 1094.20   705.3 1094.98   717.4 1097.81   741.4 1110.07   783.7 1123.43
   837.7 1141.87   922.0 1167.95   990.1 1184.00  1042.3 1200.90  1067.1 1210.46
#Mann= 3 , 0 , 0
       0     0.1       0   573.3   0.045       0   588.3     0.1       0
Bank Sta=   573.3,   588.3
Exp/Cntr=0.3,0.1

Type RM Length L Ch R = 1 ,2215.3,616.97,606.406,599.309
XS GIS Cut Line= 3
     1756829.792      230081.523     1757468.350      230102.641
     1758083.833      230122.177
#Sta/Elev= 30
       0 1094.90    26.7 1091.73    63.5 1084.68   155.5 1059.45   181.1 1053.96
   193.0 1052.48   204.9 1052.83   228.7 1056.95   247.5 1057.33   264.3 1056.14
   311.8 1050.13   347.4 1042.51   429.7 1042.59   549.4 1040.58   580.9 1040.88
   608.8 1042.88   631.8 1040.95   646.8 1042.05   699.9 1058.73   739.5 1073.17
   775.1 1083.57   798.8 1085.25   834.5 1093.30   883.9 1102.35   941.4 1112.25
   977.0 1116.88  1036.4 1128.12  1119.6 1142.28  1178.3 1148.44  1254.7 1161.57
#Mann= 3 , 0 , 0
       0     0.1       0   631.8   0.045       0   646.8     0.1       0
Bank Sta=   631.8,   646.8
Exp/Cntr=0.3,0.1

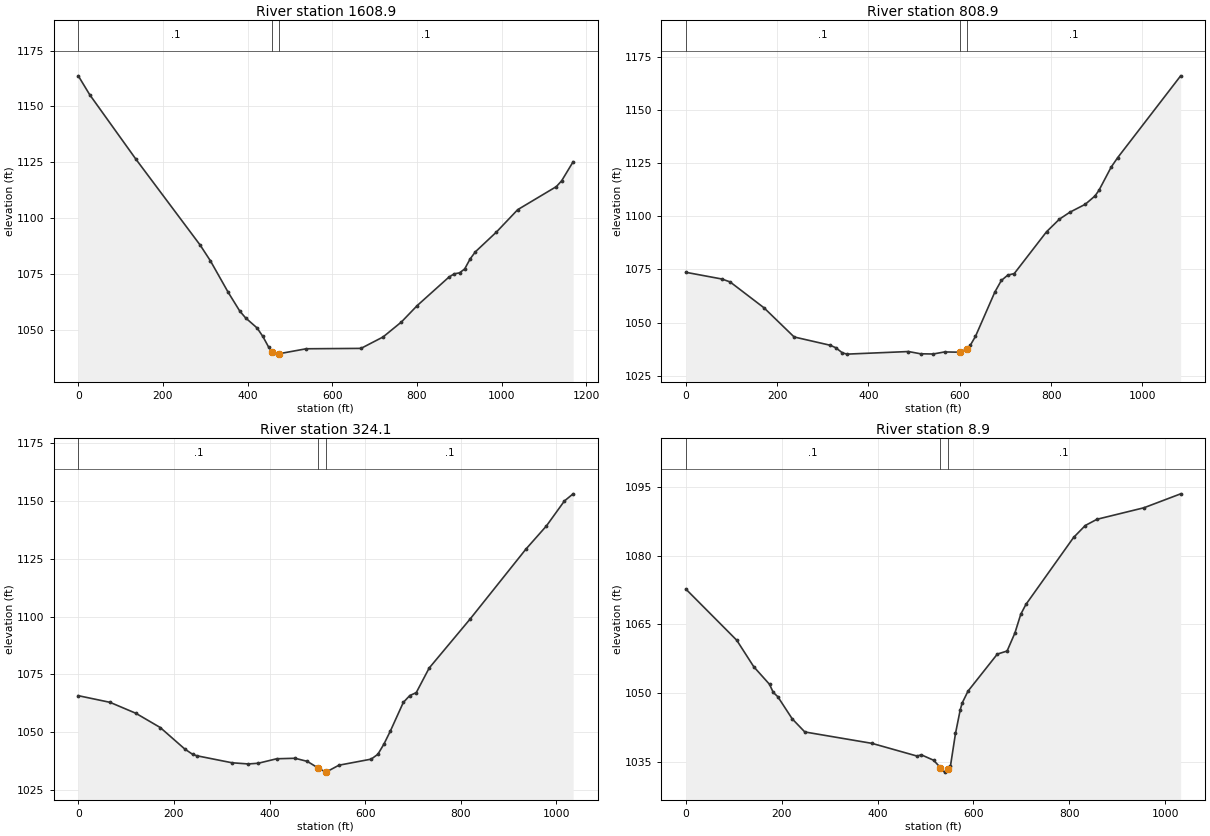
Type RM Length L Ch R = 1 ,1608.9,797.901,800,794.472
XS GIS Cut Line= 3
     1756868.516      230736.677     1757274.579      230507.648
     1757942.776      230290.060
#Sta/Elev= 30
       0 1163.67    27.1 1155.18   136.1 1126.32   287.8 1087.85   312.0 1080.81
   354.2 1066.63   381.5 1058.25   395.1 1055.23   422.4 1050.69   436.0 1046.88
   449.6 1042.13   458.7 1039.90   470.0 1038.97   473.7 1039.13   538.4 1041.37
   667.8 1041.54   720.0 1046.67   763.2 1053.36   800.6 1060.73   875.0 1073.40
   888.0 1074.95   900.5 1075.38   912.7 1077.13   925.5 1081.60   938.0 1084.82
   987.7 1093.67  1037.9 1103.69  1129.3 1114.04  1141.8 1116.65  1168.9 1125.18
#Mann= 3 , 0 , 0
       0     0.1       0   458.7   0.045       0   473.7     0.1       0
Bank Sta=   458.7,   473.7
Exp/Cntr=0.3,0.1

Type RM Length L Ch R = 1 ,808.9,483.603,484.78,486.899
XS GIS Cut Line= 3
     1757177.067      231068.908     1757724.869      230805.076
     1758124.091      230546.593
#Sta/Elev= 30
       0 1073.66    79.0 1070.50    96.9 1069.14   171.3 1056.94   237.2 1043.24
   316.2 1039.34   328.1 1038.21   342.6 1035.81   352.7 1035.17   487.6 1036.39
   513.9 1035.33   541.6 1035.23   566.6 1036.20   600.5 1036.08   615.5 1037.54
   622.7 1039.25   634.3 1043.53   676.7 1064.37   690.9 1069.81   705.0 1072.33
   719.2 1073.06   789.9 1092.73   818.2 1098.67   841.1 1101.94   874.8 1105.66
   895.9 1109.56   904.5 1112.15   931.3 1123.10   945.5 1127.54  1083.6 1166.07
#Mann= 3 , 0 , 0
       0     0.1       0   600.5   0.045       0   615.5     0.1       0
Bank Sta=   600.5,   615.5
Exp/Cntr=0.3,0.1

Type RM Length L Ch R = 1 ,324.1,319.7,315.22,320.753
XS GIS Cut Line= 3
     1757350.679      231460.952     1757817.700      231271.081
     1758285.370      231020.068
#Sta/Elev= 30
       0 1065.85    66.4 1062.97   120.2 1058.27   171.4 1052.10   222.7 1042.82
   239.5 1040.47   248.3 1039.89   321.5 1036.88   355.5 1036.37   376.5 1036.68
   414.9 1038.61   453.4 1038.82   479.0 1037.48   502.3 1034.53   517.3 1032.92
   518.1 1032.84   545.1 1035.83   612.5 1038.45   626.5 1040.54   639.4 1045.02
   652.8 1050.65   679.8 1062.95   693.3 1065.91   706.8 1067.16   733.7 1077.75
   819.5 1098.96   935.9 1129.07   979.1 1139.16  1016.7 1149.93  1034.9 1153.00
#Mann= 3 , 0 , 0
       0     0.1       0   502.3   0.045       0   517.3     0.1       0
Bank Sta=   502.3,   517.3
Exp/Cntr=0.3,0.1

Type RM Length L Ch R = 1 ,8.9,0.784,8.901,8.901
XS GIS Cut Line= 3
     1757607.281      231754.727     1758054.662      231454.406
     1758533.655      231334.655
#Sta/Elev= 30
       0 1072.71   106.3 1061.54   141.8 1055.76   174.7 1051.92   182.5 1050.15
   191.8 1049.25   222.1 1044.39   248.3 1041.54   388.6 1039.05   482.6 1036.28
   491.3 1036.56   516.9 1035.38   531.3 1033.78   539.8 1032.78   546.3 1033.52
   552.1 1034.03   562.7 1041.21   572.5 1046.31   576.5 1047.81   588.8 1050.44
   650.0 1058.52   670.4 1059.19   686.7 1063.12   698.9 1067.20   709.6 1069.34
   809.1 1083.95   833.5 1086.56   858.0 1087.92   955.9 1090.43  1032.6 1093.47
#Mann= 3 , 0 , 0
       0     0.1       0   531.3   0.045       0   546.3     0.1       0
Bank Sta=   531.3,   546.3
Exp/Cntr=0.3,0.1